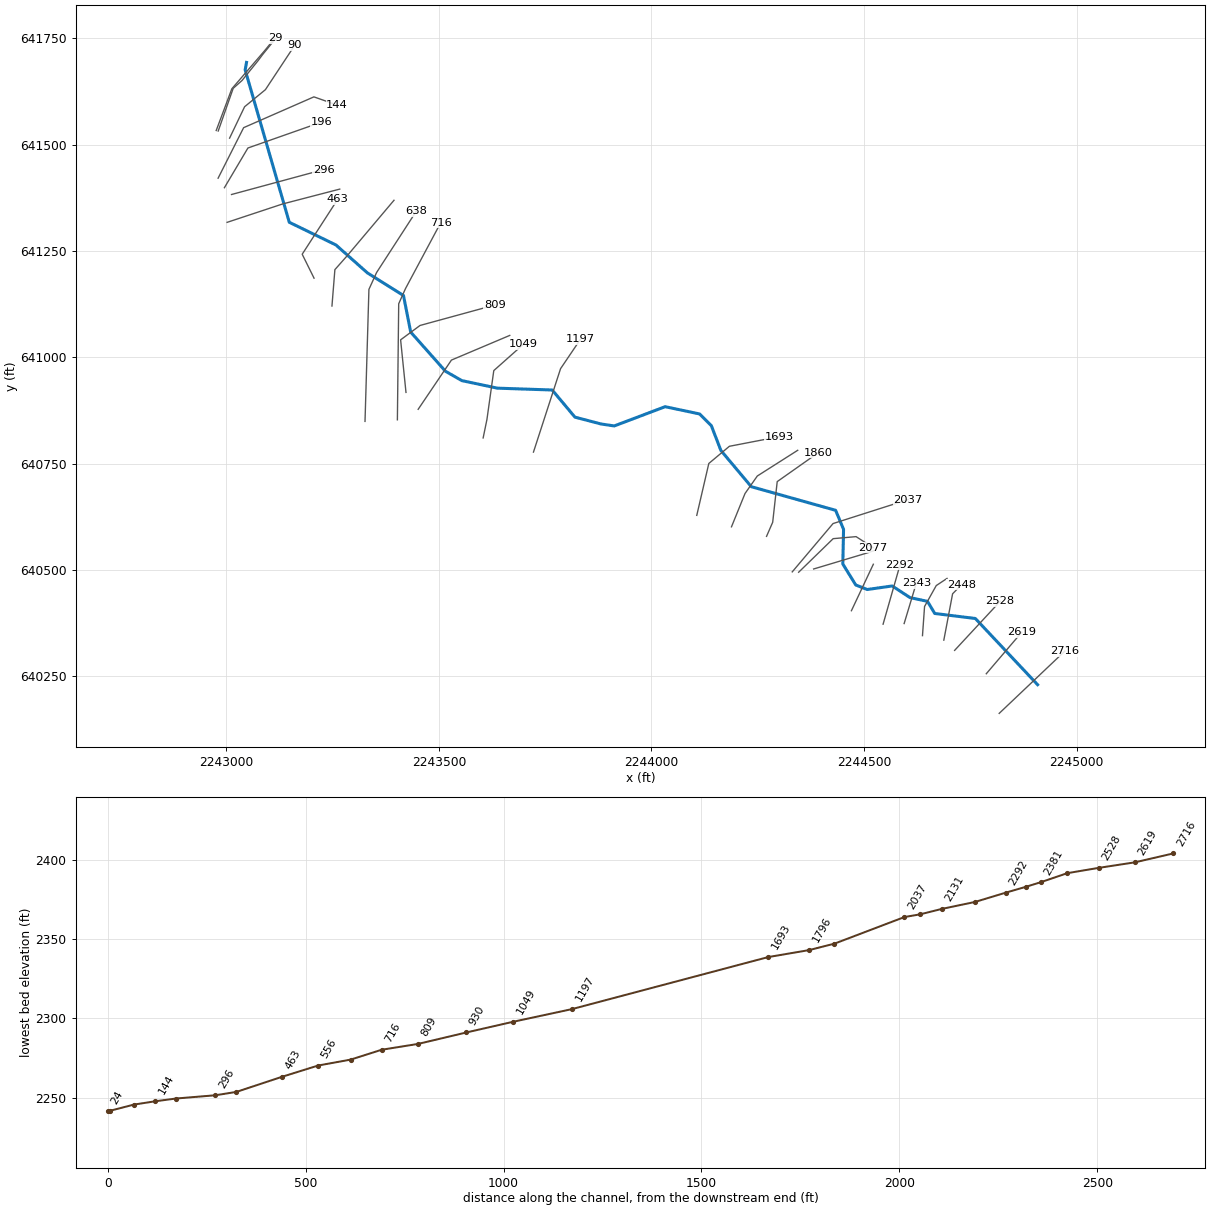
--- SPICERN.prj (project) ---

Proj Title=SPICERN
Current Plan=p01
Default Exp/Contr=0,0
English Units
Geom File=g01
Flow File=f01
Plan File=p01
BEGIN DESCRIPTION:
----------MODEL BY WOOD PLC 2022----------
AFH study:Spice Run
Randolph County, WV
HEC-RAS Version: RAS 6.2
Vertical Datum: NAVD88
Projection: NAD 1983 StatePlane West Virginia S FIPS 4702 (US Feet)
Terrain: 1-meter LIDAR (FEMA Region III 3DEP collected 2016-2018)
Land Use: 2019 NLCD
Hydrologic Method:
WV SIR2010-5033 regression equations
Additional Model Notes:
Dominant flow path issue at confluence with SUGARRN, but because of the coincident peak situation with SUGARRN, as well as NHD lines naming the reach DS of the confluence as SPICERN, the model was not split up.
XS 349 used as shared XS with SUGARRN
END DESCRIPTION:
DSS Export Rating Curves= 0
DSS Export Rating Curve Sorted= 0
DSS Export Volume Flow Curves= 0
DXF OffsetX= 0
DXF OffsetY= 0
DXF ScaleX= 0
DXF ScaleY= 0

--- SPICERN.p01 (plan) ---

Plan Title=Floodplain
Program Version=6.20
Short Identifier=Floodplain
Geom File=g01
Flow File=f01
Subcritical Flow
K Sum by GR= 0
Std Step Tol= 0.01
Critical Tol= 0.01
Num of Std Step Trials= 20
Max Error Tol= 0.3
Flow Tol Ratio= 0.001
Split Flow NTrial= 30
Split Flow Tol= 0.02
Split Flow Ratio= 0.02
Log Output Level= 0
Friction Slope Method= 1
Unsteady Friction Slope Method= 2
Unsteady Bridges Friction Slope Method= 1
Parabolic Critical Depth
Global Vel Dist= 0 , 0 , 0
Global Log Level= 0
CheckData=True
Encroach Param=-1 ,0,0, 0
Mapping Interval=1HOUR
Computation Time Step Use Courant=        0
Computation Time Step Use Time Series=    0
Computation Time Step Count To Double=0
Computation Time Step Max Doubling=0
Computation Time Step Max Halving=0
Computation Time Step Residence Courant=0
Run HTab= 0
Run UNet= 0
Run Sediment= 0
Run PostProcess= 0
Run WQNet= 0
Run RASMapper=-1
UNET Theta= 0
UNET Theta Warmup= 0
UNET ZTol= 0
UNET ZSATol= 0
UNET MxIter= 0
UNET Max Iter WO Improvement= 0
UNET MaxInSteps= 0
UNET DtIC= 0
UNET DtMin= 0
UNET MaxCRTS= 0
UNET WFStab= 0
UNET SFStab= 0
UNET WFX= 1
UNET SFX= 1
UNET Gravity=32.174
UNET 1D Methodology=Finite Difference
UNET DSS MLevel= 1
UNET Pardiso=0
UNET DZMax Abort= 0
UNET Use Existing IB Tables= 0
UNET Froude Reduction=False
UNET Froude Limit= 0
UNET Froude Power= 0
UNET D1 Cores= 0
UNET WindReference=Eulerian
UNET WindDragFormulation=Hsu (1988)
UNET D2 Coriolis=0
UNET D2 Cores= 0
UNET D2 Theta= 1
UNET D2 Theta Warmup= 1
UNET D2 Z Tol= 0.01
UNET D2 Volume Tol= 0.01
UNET D2 Max Iterations= 20
UNET D2 Equation= 0
UNET D2 RampUpFraction=0.1
UNET D2 TimeSlices= 1
UNET D2 Turbulence Formulation=Non-Conservative (original)
UNET D2 Eddy Viscosity=0.3
UNET D2 Transverse Eddy Viscosity=0.1
UNET D2 Smagorinsky Mixing=0
UNET D2 BCVolumeCheck=0
UNET D2 Cores=0
UNET D2 SolverType=PARDISO (Direct)
UNET D2 Minimum Iterations= 2147483647
UNET D2 Maximum Iterations= 2147483647
UNET D2 Restart Number= 10
UNET D2 Relaxation Coeff=1.3
UNET D2 SOR Precondition Iterations= 10
UNET D2 ILUT Maximum Fill= 8
UNET D2 ILUT Tolerance=1E-08
UNET D1D2 MaxIter= 0
UNET D1D2 ZTol=0.01
UNET D1D2 QTol=0.1
UNET D1D2 MinQTol=1
Write IC File= 0
Write IC File at Fixed DateTime=0
Write IC File at Sim End=0
Echo Input=False
Echo Parameters=False
Echo Output=False
Write Detailed= 0
HDF Write Warmup=0
HDF Write Time Slices=0
HDF Flush=0
HDF Compression= 1
HDF Chunk Size= 1
HDF Spatial Parts= 1
HDF Use Max Rows=0
HDF Fixed Rows= 1
Calibration Method= 0
Calibration Iterations= 20
Calibration Max Change=0.05
Calibration Tolerance=0.2
Calibration Maximum=1.5
Calibration Minimum=0.5
Calibration Optimization Method= 1
WQ AD Non Conservative
WQ ULTIMATE=-1
WQ Max Comp Step=1HOUR
WQ Output Interval=15MIN
WQ Output Selected Increments= 0
WQ Output face flow=0
WQ Output face velocity=0
WQ Output face area=0
WQ Output face dispersion=0
WQ Output cell volume=0
WQ Output cell surface area=0
WQ Output cell continuity=0
WQ Output cumulative cell continuity=0
WQ Output face conc=0
WQ Output face dconc_dx=0
WQ Output face courant=0
WQ Output face peclet=0
WQ Output face adv mass=0
WQ Output face disp mass=0
WQ Output cell mass=0
WQ Output cell source sink temp=0
WQ Output nsm pathways=0
WQ Output nsm derived pathways=0
WQ Create Restart=0
WQ Fixed Restart=0
WQ System Summary=0
WQ Write To DSS=0
Sorting and Armoring Iterations= 10
XS Update Threshold= 0.02
Bed Roughness Predictor= 0
Hydraulics Update Threshold= 0.02
Energy Slope Method= 1
Volume Change Method= 1
Sediment Retention Method= 0
Sediment TS Multiplier= 1
Warm Up Method= 0
XS Weighting Method= 0
Number of US Weighted Cross Sections= 1
Number of DS Weighted Cross Sections= 1
Upstream XS Weight=0
Main XS Weight=1
Downstream XS Weight=0
Number of DS XS's Weighted with US Boundary= 1
Upstream Boundary Weight= 1
Weight of XSs Associated with US Boundary= 0
Number of US XS's Weighted with DS Boundary= 1
Downstream Boundary Weight= 0.5
Weight of XSs Associated with DS Boundary= 0.5
Percentile Method= 0
Sediment Output Level= 3
Mass or Volume Output= 0
Output Increment Type= 1
Profile and TS Output Increment= 1
Transport Output Increment 1
XS Output Flag= 0
XS Output Increment= 10
Read HDF5 Sediment Hotstart= 0
Sediment Hotstart Type= 0
Write Gradation File= 0
Read Gradation Hotstart= 0
Write HDF5 File= 1
Write Binary Output= 1
Write DSS Sediment File= 0
DSS Sediment Output Type= 1
SV Curve= 0
Specific Gage Flag= 0
Subcell Erosion Methods= 0
Subcell Deposition Methods= 0
Advection Scheme= 1
Matrix Solver= 0
Implicit Weighting Factor= 1
Maximum Outer Loop Convergence Iterations= 5
Convergence Maximum Absolute= 0.001
Convergence RMSE= 0.0001
Grain Fractions Max Abs Error= 0.001
Max Subgrid Regions= 1
Max Subgrid Length Scale= 3.402823E+38
Initial Layer Thickness= 3.402823E+38
Min Layer Thickness= 3.402823E+38
Max Layer Thickness= 3.402823E+38
Number of Layers= 5

--- SPICERN.f01 (steady flow) ---

Flow Title=Flow
Program Version=6.20
Number of Profiles= 1
Profile Names=P100yr
River Rch & RM=SPICERN,Main            ,2716
     325
River Rch & RM=SPICERN,Main            ,349
     590
Boundary for River Rch & Prof#=SPICERN,Main            , 1
Up Type= 0
Dn Type= 3
Dn Slope=0.04404
DSS Import GetInterval= 0
DSS Import GetPeak= 0
DSS Import FillOption= 0

--- SPICERN.g01 (geometry) ---

Geom Title=Geometry
Program Version=6.20

River Reach=SPICERN         ,Main
Reach XY= 30
2244908.23739329640229.6402901712244761.77400002      640385.434
2244666.27579343 640397.197099762244649.19621402640425.726066425
2244608.04200004640434.6100000292244566.28402516640461.938012749
2244507.36499998640453.6010000112244480.41599999640464.297999993
2244450.05500004      640513.6032244451.79200004640595.200000003
2244433.12800002640639.9050000012244234.77800003640695.460000008
2244163.22232509 640780.701774882244140.76351325640838.966747254
2244113.16671336640866.5635471792244032.08333215640883.633732691
2243912.31908725640838.3466283832243881.04500003640843.030000016
     2243819.847640859.0890000162243766.46200001640922.891000018
2243637.55500004640927.2310000062243553.78800003640945.025999993
2243515.15999998640967.1620000152243433.56200002641059.175999999
2243416.63499999641145.1130000052243331.56600004641198.499000013
     2243257.781641264.0370000152243147.97200003641317.422000006
2243044.18347982641675.8337780982243047.39499998641693.491999999

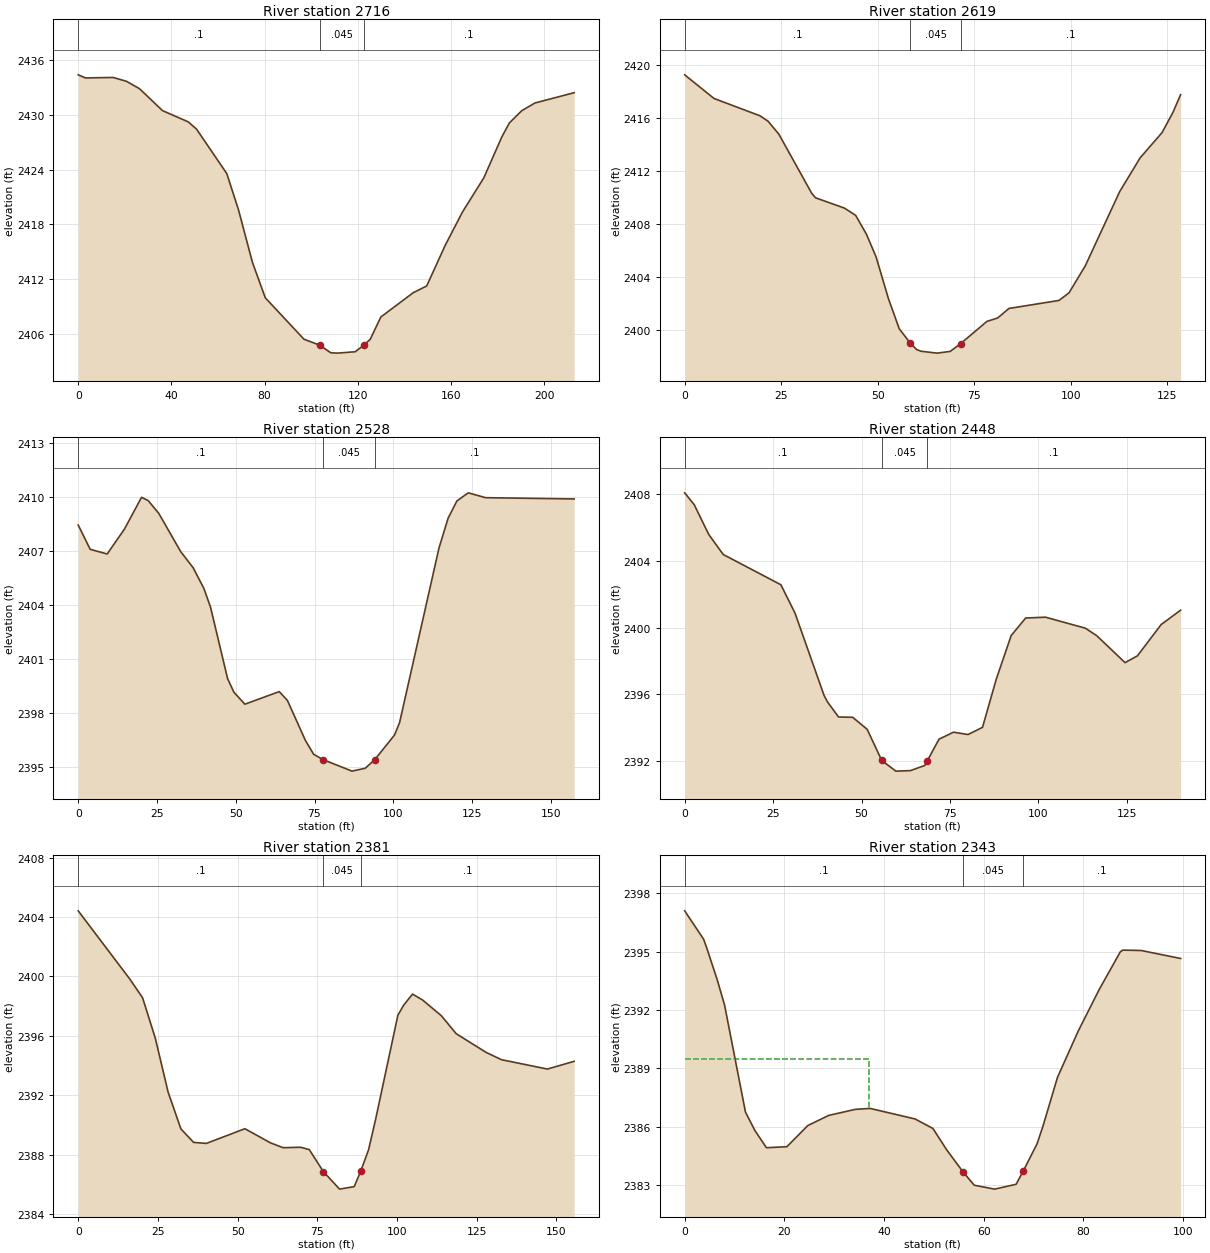
Type RM Length L Ch R = 1 ,2716    ,96.5,97.6,98.3
XS GIS Cut Line= 2
  2244817.902264640162.2290020242244972.38557804640308.793827039
#Sta/Elev= 30
       0  2434.4     3.1 2434.06      15 2434.11    20.7 2433.69    26.3 2432.88
    36.2 2430.47    47.2 2429.24    50.8 2428.44    63.8 2423.55    68.8 2419.59
    74.8 2413.81    80.3 2409.93    96.9 2405.38   103.72404.722   108.4 2403.89
   111.2 2403.85   118.9    2404   122.5  2404.7   125.4 2405.38   129.9 2407.81
   143.8 2410.48   149.6 2411.22   157.5 2415.66     165 2419.36   174.1 2423.08
   181.9 2427.61   185.1 2429.12   190.4 2430.46   196.1 2431.31   212.9 2432.44
#Mann= 3 ,-1,0
       0      .1       0   103.7    .045       0   122.5      .1       0
Bank Sta=103.7,122.5
XS Rating Curve= 0 ,0
Exp/Cntr(USF)=0,0
Exp/Cntr=0.3,0.1

Type RM Length L Ch R = 1 ,2619    ,90.2,90.3,90.1
XS GIS Cut Line= 2
2244787.51222186640255.4341793942244870.93421849640353.143921308
#Sta/Elev= 30
       0 2419.29     7.6  2417.5    19.5 2416.19    21.6 2415.78    24.4  2414.8
    32.9 2410.33    33.9 2409.98    41.4  2409.2    44.3 2408.65    47.1 2407.22
    49.6  2405.5    52.8 2402.34    55.6 2400.06    58.5 2398.96    60.1 2398.49
    61.3 2398.36    65.4 2398.22    68.8 2398.35    71.52398.938    78.3 2400.62
    81.1 2400.88      84  2401.6      97 2402.21    99.6 2402.79   103.8 2404.83
   112.7 2410.44     118    2413   123.7 2414.92   126.5 2416.44   128.5 2417.79
#Mann= 3 ,-1,0
       0      .1       0    58.5    .045       0    71.5      .1       0
Bank Sta=58.5,71.5
XS Rating Curve= 0 ,0
Exp/Cntr(USF)=0,0
Exp/Cntr=0.3,0.1

Type RM Length L Ch R = 1 ,2528    ,75,80.2,83.9
XS GIS Cut Line= 2
2244713.06689839640310.411540872 2244820.1354505640425.807647029
#Sta/Elev= 30
       0 2408.46     3.8 2407.11     9.2 2406.85    14.7 2408.24    20.1    2410
    22.2 2409.82    25.6  2409.1    32.5 2406.99    36.5 2406.08    39.9 2404.93
      42 2403.89    47.4 2399.93    49.4 2399.17    52.9  2398.5    63.8  2399.2
    66.4 2398.71    72.1 2396.49    74.7 2395.72    77.7 2395.42    86.9 2394.78
    91.1 2394.94    94.12395.413   100.4 2396.79     102 2397.48   114.5 2407.18
   117.4 2408.84   120.2  2409.8   123.8 2410.25   129.3 2409.98   157.4 2409.91
#Mann= 3 ,-1,0
       0      .1       0    77.7    .045       0    94.1      .1       0
Bank Sta=77.7,94.1
XS Rating Curve= 0 ,0
Exp/Cntr(USF)=0,0
Exp/Cntr=0.3,0.1

Type RM Length L Ch R = 1 ,2448    ,68.6,67.5,64.4
XS GIS Cut Line= 4
2244687.61928225640334.4946810822244692.06587238640357.723984507
2244708.27163098 640443.47954201 2244728.6867906640464.400016564
#Sta/Elev= 30
       0 2408.06     2.7 2407.35     6.8 2405.57    10.9 2404.37    27.2 2402.56
    31.2 2400.86    39.4 2395.94    40.4 2395.54    43.5 2394.65    47.5 2394.63
    51.6 2393.91    55.7 2392.05    59.7 2391.41    63.8 2391.44    67.9 2391.75
    68.62392.032    71.9 2393.32      76 2393.74    80.1  2393.6    84.2 2394.03
    88.1 2396.92    92.3 2399.52    96.4 2400.57     102 2400.62   113.3 2399.96
   116.5 2399.51   124.5  2397.9     128 2398.31   134.7 2400.18   140.2 2401.04
#Mann= 3 ,-1,0
       0      .1       0    55.7    .045       0    68.6      .1       0
Bank Sta=55.7,68.6
XS Rating Curve= 0 ,0
Exp/Cntr(USF)=0,0
Exp/Cntr=0.3,0.1

Type RM Length L Ch R = 1 ,2381    ,36.5,37.6,38.9
XS GIS Cut Line= 4
2244637.43643608640345.0561520782244642.33012825 640413.64521211
2244669.80494204640462.8390132182244695.19017881640479.696785622
#Sta/Elev= 30
       0 2404.42    16.2 2399.82    20.2 2398.56    24.2 2395.83    28.2 2392.21
    32.2 2389.74    32.6 2389.64    36.2 2388.82    40.2 2388.75    52.3 2389.74
    60.3 2388.79    64.3 2388.46    69.8 2388.49    72.5 2388.33   76.92 2386.85
      82 2385.67    86.6 2385.84    88.6 2386.86    91.1 2388.32    93.3 2390.36
   100.3 2397.39   102.1 2398.06   104.9 2398.81     108 2398.42   113.9 2397.36
   118.6 2396.14     128 2394.88   132.8 2394.39   147.2 2393.76   155.6 2394.28
#Mann= 3 ,0,0
       0      .1       0   76.92    .045       0    88.6      .1       0
Bank Sta=76.92,88.6
XS Rating Curve= 0 ,0
Exp/Cntr(USF)=0,0
Exp/Cntr=0.3,0.1

Type RM Length L Ch R = 1 ,2343    ,50.8,50.9,50.8
XS GIS Cut Line= 2
2244594.29689413640373.5245050892244623.03170642640468.833040908
#Sta/Elev= 30
       0  2397.1     3.8 2395.64     4.4 2395.21     6.5 2393.58       8 2392.26
    12.2 2386.75    14.1  2385.8    16.4 2384.92    20.5 2384.97    24.7 2386.06
    28.9 2386.58    34.2 2386.89    37.2 2386.94    46.2  2386.4    49.8 2385.91
    52.6  2384.8    55.8 2383.69    58.1 2382.99    62.2 2382.79    66.5 2383.04
    67.92383.707    70.7 2385.12    71.9 2386.04    74.8 2388.54      79 2390.94
    83.2 2393.07    87.4 2394.99    87.9 2395.08    91.6 2395.06    99.5 2394.65
#Mann= 3 ,-1,0
       0      .1       0    55.8    .045       0    67.9      .1       0
#XS Ineff= 2 , 0
           36.91 2389.46
Permanent Ineff=
       F       F
Bank Sta=55.8,67.9
XS Rating Curve= 0 ,0
Exp/Cntr(USF)=0,0
Exp/Cntr=0.3,0.1

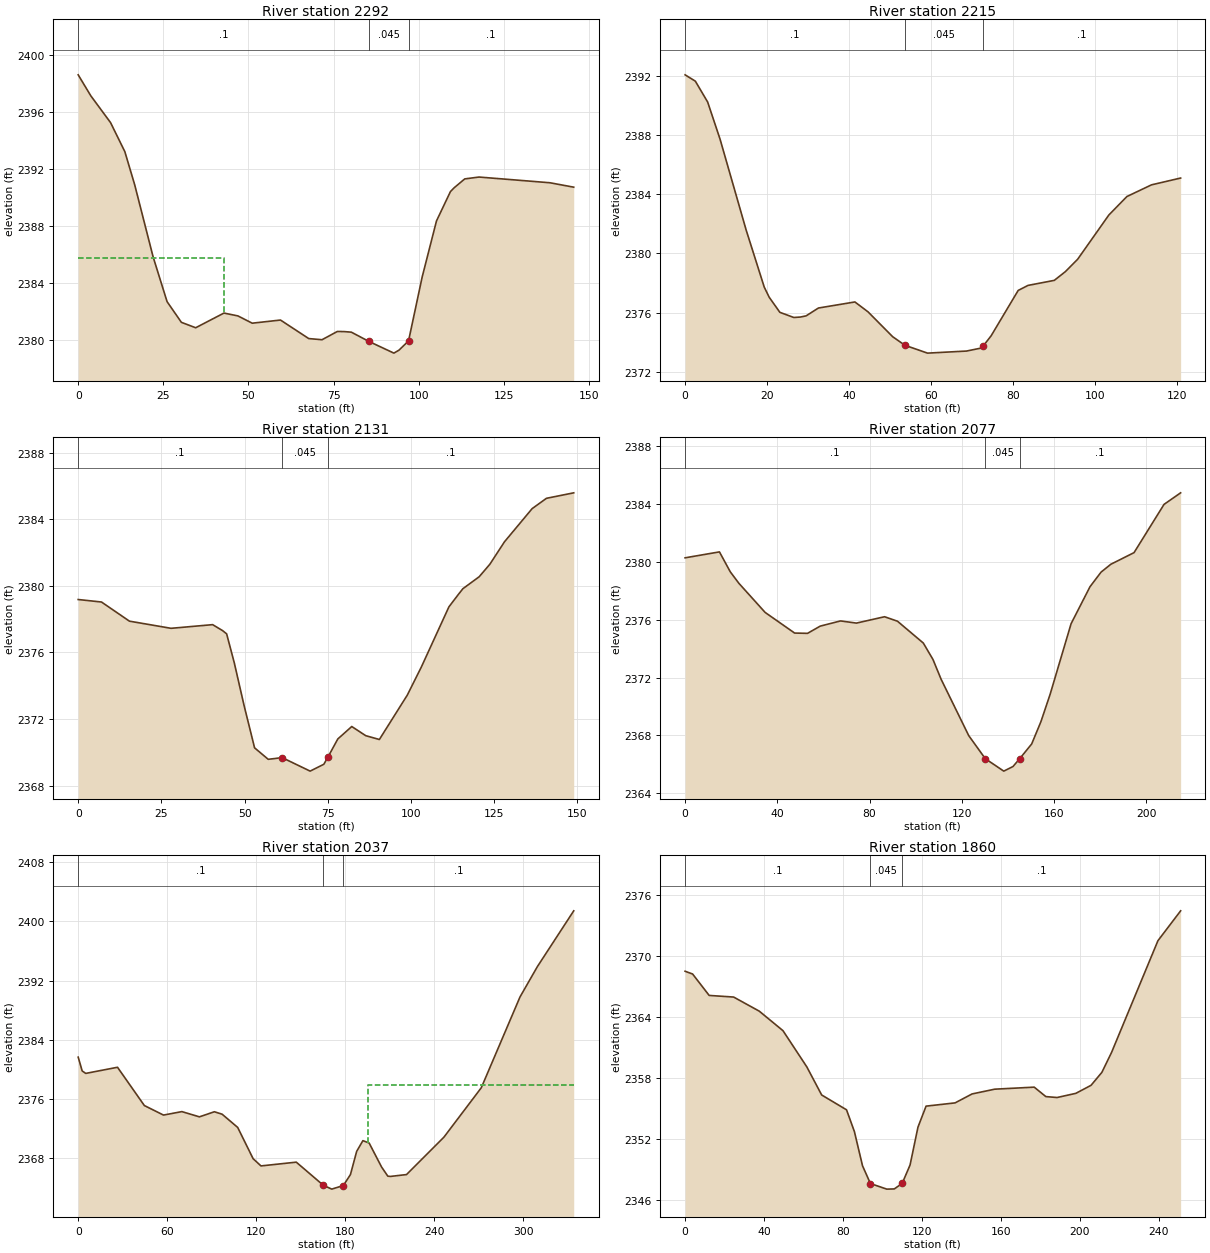
Type RM Length L Ch R = 1 ,2292    ,77,77.5,71.2
XS GIS Cut Line= 2
2244544.77766344640372.0505604662244584.76981287640511.924331681
#Sta/Elev= 30
       0 2398.62     3.7 2397.15     9.5 2395.27    13.7 2393.23    16.6  2390.9
      22 2385.85    26.1 2382.71    30.3 2381.26    34.5 2380.88    42.8 2381.91
    46.9 2381.71    51.1  2381.2    59.4 2381.42    67.7 2380.12    71.6 2380.04
    76.1 2380.62    78.1 2380.61    80.2 2380.57    85.42379.917    92.7  2379.1
    94.2 2379.31      972379.958     101 2384.44   105.2 2388.37   109.3 2390.43
   110.4  2390.7   113.5 2391.32   117.7 2391.45   138.5 2391.05   145.5 2390.74
#Mann= 3 ,-1,0
       0      .1       0    85.4    .045       0      97      .1       0
#XS Ineff= 2 , 0
           42.67 2385.76
Permanent Ineff=
       F       F
Bank Sta=85.4,97
XS Rating Curve= 0 ,0
Exp/Cntr(USF)=0,0
Exp/Cntr=0.3,0.1

Type RM Length L Ch R = 1 ,2215    ,89,84.1,74.9
XS GIS Cut Line= 2
2244470.30711366   640403.7365012244521.80217331640512.985688326
#Sta/Elev= 30
       0 2392.08     2.5 2391.65     5.5 2390.24     8.5 2387.75    14.9 2381.57
    19.3 2377.72    20.5 2377.04    23.1 2376.02    26.5 2375.67    28.1  2375.7
    29.5 2375.78    32.5 2376.31    41.4 2376.72    44.6 2376.05    50.6 2374.37
    53.6 2373.79    59.1 2373.26    68.6  2373.4    72.3 2373.61    72.72373.753
    74.6 2374.43    81.2  2377.5    83.6 2377.84      90 2378.18    92.7 2378.77
    95.7 2379.61   103.3  2382.6   107.7 2383.85   113.7 2384.64   120.8  2385.1
#Mann= 3 ,-1,0
       0      .1       0    53.6    .045       0    72.7      .1       0
Bank Sta=53.6,72.7
XS Rating Curve= 0 ,0
Exp/Cntr(USF)=0,0
Exp/Cntr=0.3,0.1

Type RM Length L Ch R = 1 ,2131    ,55.6,53.5,53.1
XS GIS Cut Line= 3
2244381.44582951640501.8801703412244507.36752895640539.623465465
2244523.90700186640545.056614835
#Sta/Elev= 30
       0 2379.18       7 2379.03    15.4 2377.88    27.9 2377.45    40.4 2377.67
    43.4 2377.31    44.6 2377.12    46.9 2375.38    49.8 2372.85      53 2370.27
    57.1 2369.58    61.3 2369.68    69.7 2368.87    73.8 2369.28      752369.697
      78  2370.8    82.2 2371.55    86.4    2371    90.5 2370.77    98.9 2373.44
   103.1 2375.12   111.4 2378.74   114.1 2379.45   115.6 2379.83   120.5 2380.55
   123.7  2381.3   128.1 2382.65   136.4 2384.64   140.7 2385.26   148.9 2385.59
#Mann= 3 ,-1,0
       0      .1       0    61.3    .045       0      75      .1       0
Bank Sta=61.3,75
XS Rating Curve= 0 ,0
Exp/Cntr(USF)=0,0
Exp/Cntr=0.3,0.1

Type RM Length L Ch R = 1 ,2077    ,39.4,40.4,42.3
XS GIS Cut Line= 4
 2244346.1409335640494.196473382 2244427.3664453640573.208474456
2244481.26149972 640577.97494047 2244521.1401299640552.263718376
#Sta/Elev= 30
       0 2380.29    14.9  2380.7    19.6 2379.32    23.3 2378.53    34.7 2376.51
    47.5 2375.08    53.1 2375.06    58.6 2375.56    67.4 2375.92    74.3 2375.77
    86.5 2376.21    92.1  2375.9   103.3 2374.39   107.5 2373.25     111 2371.89
     123 2367.98   130.2 2366.38   138.2 2365.52   142.2 2365.84   145.1 2366.38
   150.3  2367.4   154.3 2368.94   158.3 2370.84   167.4 2375.73   175.6 2378.29
   180.4  2379.3   184.6 2379.84   194.7 2380.65   207.7 2383.99   214.9 2384.79
#Mann= 3 ,-1,0
       0      .1       0   130.2    .045       0   145.1      .1       0
Bank Sta=130.2,145.1
XS Rating Curve= 0 ,0
Exp/Cntr(USF)=0,0
Exp/Cntr=0.3,0.1

Type RM Length L Ch R = 1 ,2037    ,170.3,176.6,186.2
XS GIS Cut Line= 3
2244331.07025886640495.0807401742244427.09219772640608.744333376
2244603.52098437640665.078264298
#Sta/Elev= 30
       0 2381.63     2.7 2379.76     5.1 2379.43    26.5 2380.26    44.6 2375.08
    57.5 2373.79    69.9 2374.26    81.7 2373.55    91.8 2374.24      97 2373.91
   107.5 2372.12   117.9 2367.89   123.2 2366.91     147 2367.42   165.22364.296
   170.9 2363.77  178.73 2364.26   183.5 2365.74   187.7 2368.88   191.9 2370.33
   196.1 2370.01   204.5 2366.76   208.7 2365.52   210.5 2365.49   221.3 2365.74
   246.5  2370.8   271.7 2377.49   297.8 2389.78   309.5 2393.88     334 2401.43
#Mann= 3 ,0,0
       0      .1       0   165.2    .045       0  178.73      .1       0
#XS Ineff= 2 , 0
                           195.2         2377.84
Permanent Ineff=
       F       F
Bank Sta=165.2,178.73
XS Rating Curve= 0 ,0
Exp/Cntr(USF)=0,0
Exp/Cntr=0.3,0.1

Type RM Length L Ch R = 1 ,1860    ,67,63.9,59.7
XS GIS Cut Line= 4
2244270.64199601640578.6474608492244285.09625054640611.838712002
2244295.72459251640707.4059458762244392.84953402640775.799277275
#Sta/Elev= 30
       0 2368.48     3.8 2368.21    12.2  2366.1    24.6 2365.94    37.6 2364.55
    49.6 2362.63    61.7 2359.06    69.2  2356.3    81.8 2354.84    85.8 2352.69
    89.9 2349.33    93.9 2347.58   102.2 2347.03     106 2347.05     110 2347.59
     114 2349.41     118 2353.13   122.1  2355.2   136.8 2355.52   145.4  2356.4
   156.9 2356.87   176.9 2357.07   182.8 2356.14   188.5 2356.05     198 2356.46
   205.7 2357.25   211.2 2358.53   216.1 2360.49   239.6 2371.49   251.1 2374.43
#Mann= 3 ,-1,0
       0      .1       0    93.9    .045       0     110      .1       0
Bank Sta=93.9,110
XS Rating Curve= 0 ,0
Exp/Cntr(USF)=0,0
Exp/Cntr=0.3,0.1

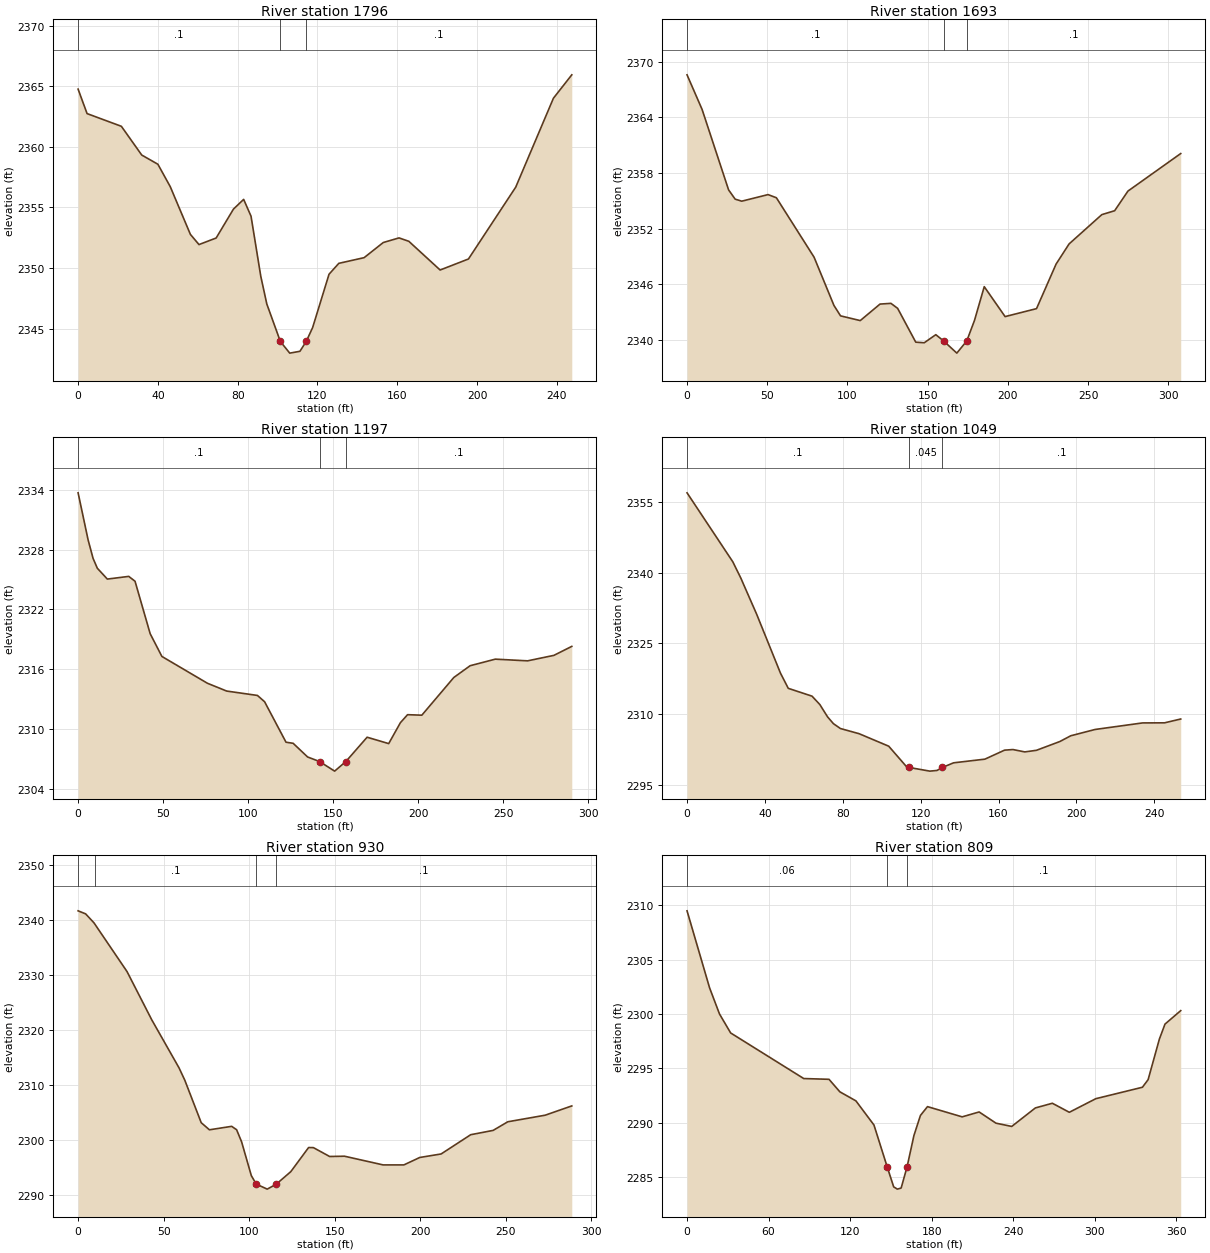
Type RM Length L Ch R = 1 ,1796    ,104.8,103.6,101.4
XS GIS Cut Line= 4
 2244188.1708684640601.0482388612244219.99535881640679.405927837
2244248.93083152640720.6264534032244343.94158444640781.078217734
#Sta/Elev= 30
       0 2364.77     4.5 2362.75    21.7  2361.7    31.9 2359.33      40 2358.57
    46.2 2356.72    56.3 2352.78    60.6 2351.94    69.2 2352.48    77.9 2354.87
      83 2355.67    86.7 2354.28    91.6 2349.31    94.6 2347.04   101.4 2343.94
   106.1 2342.98   111.2 2343.13   114.4 2343.95   117.6  2345.1   125.8 2349.49
   130.7 2350.39   143.4 2350.86     153 2352.11   160.9 2352.49   165.8 2352.21
   181.5 2349.84   195.7 2350.75   219.4 2356.68   238.3 2364.02   247.5 2365.95
#Mann= 3 ,-1,0
       0      .1       0   101.4    .045       0   114.4      .1       0
Bank Sta=101.4,114.4
XS Rating Curve= 0 ,0
Exp/Cntr(USF)=0,0
Exp/Cntr=0.3,0.1

Type RM Length L Ch R = 1 ,1693    ,491.3,496,499.5
XS GIS Cut Line= 4
2244106.50460008640627.9947295132244134.82884332640750.066145255
2244183.22121096640790.486061858 2244300.4742824640813.121917073
#Sta/Elev= 30
       0 2368.59     9.4 2364.85    25.9 2356.18      30 2355.18    34.1 2354.96
    50.5 2355.67    55.7 2355.33    79.2 2348.92    91.6 2343.71    95.7 2342.59
     108 2342.08   120.3 2343.86   127.1 2343.94   131.3  2343.4   142.6 2339.75
   147.9 2339.69   155.1 2340.56     160 2339.88   168.2 2338.57   174.42339.887
   179.2 2342.09   185.3 2345.74   198.3 2342.51   217.9 2343.37   230.1 2348.18
   238.2 2350.35   258.6 2353.51   266.6 2353.93   274.9 2356.05   307.8  2360.1
#Mann= 3 ,-1,0
       0      .1       0     160    .045       0   174.4      .1       0
Bank Sta=160,174.4
XS Rating Curve= 0 ,0
Exp/Cntr(USF)=0,0
Exp/Cntr=0.3,0.1

Type RM Length L Ch R = 1 ,1197    ,145.4,147.6,147.9
XS GIS Cut Line= 3
2243722.35025513640776.8255573062243786.06909298640973.014046898
 2243833.1860558641042.655495645
#Sta/Elev= 30
       0  2333.7     5.9 2328.97     8.8 2327.13    11.3 2326.14    17.2 2325.05
    29.8 2325.32    33.5 2324.83    42.4 2319.57    49.3 2317.29    76.1  2314.6
    87.4 2313.82   105.5 2313.38   109.7 2312.75   122.3 2308.69   126.5 2308.58
     135 2307.21   142.12306.746   150.9 2305.79   157.52306.751     170 2309.19
   182.7 2308.55   189.6 2310.65   193.8 2311.45   202.2  2311.4     221 2315.18
   230.6 2316.36   245.4 2317.02   264.4 2316.85   279.9  2317.4   290.4  2318.3
#Mann= 3 ,-1,0
       0      .1       0   142.1    .045       0   157.5      .1       0
Bank Sta=142.1,157.5
XS Rating Curve= 0 ,0
Exp/Cntr(USF)=0,0
Exp/Cntr=0.3,0.1

Type RM Length L Ch R = 1 ,1049    ,121.8,118.8,115.7
XS GIS Cut Line= 4
2243603.98455874640810.1202351562243612.90693808640853.542481288
2243629.02551232640968.5515992022243698.68624334641030.405264952
#Sta/Elev= 30
       0 2356.93    23.5  2342.3    27.6 2338.86    35.8 2331.13      48 2318.66
      52 2315.44    64.2 2313.78    68.2 2312.01    72.2 2309.38    75.2 2307.94
    78.8 2306.91    88.4 2305.81   103.6 2303.16   112.6 2298.88   114.2 2298.64
   124.7 2297.87   128.4 2298.01   131.22298.651   136.9 2299.63     153 2300.41
   163.1 2302.32   167.4 2302.45   173.5 2301.95   179.5 2302.29   191.5 2304.15
   197.1 2305.37   209.6 2306.71     234  2308.1   245.3 2308.12   253.6 2308.93
#Mann= 3 ,-1,0
       0      .1       0   114.2    .045       0   131.2      .1       0
Bank Sta=114.2,131.2
XS Rating Curve= 0 ,0
Exp/Cntr(USF)=0,0
Exp/Cntr=0.3,0.1

Type RM Length L Ch R = 1 ,930     ,123.4,121.6,119.2
XS GIS Cut Line= 3
2243451.15585051640877.502216905 2243529.3673503640993.276440291
2243666.57087155641051.302355098
#Sta/Elev= 30
       0 2341.67     4.4 2341.12     9.3 2339.48    28.6 2330.64    43.1 2321.85
      59 2313.15    62.4 2310.89      72 2303.17    76.8 2301.88    89.8 2302.51
    92.7 2301.89    95.6 2299.71   101.3 2293.55   104.2 2292.01   110.6  2291.1
   115.9    2292   124.4 2294.28   134.8 2298.66   137.6 2298.64   147.1 2297.03
   155.8 2297.08   178.4  2295.5   190.5  2295.5   199.8 2296.85   212.3 2297.49
   229.6 2300.99   242.7 2301.77   251.3 2303.34   273.1 2304.53   288.7 2306.22
#Mann= 4 ,-1,0
       0     .06       0      10      .1       0   104.2    .045       0
   115.9      .1       0
Bank Sta=104.2,115.9
XS Rating Curve= 0 ,0
Exp/Cntr(USF)=0,0
Exp/Cntr=0.3,0.1

Type RM Length L Ch R = 1 ,809     ,78.6,92.3,93.7
XS GIS Cut Line= 4
2243422.48525429640917.2493105912243409.84953455641040.898853709
  2243455.522856641074.708031596 2243631.3308535641122.798106165
#Sta/Elev= 30
       0 2309.48    16.6  2302.4    23.9    2300    32.1 2298.26    85.9 2294.07
   104.5    2294   112.5 2292.85   124.3 2292.02   137.6  2289.8   147.42285.926
   152.1 2284.12   154.8 2283.91   157.6 2284.01   161.92285.926     167 2288.83
   171.8 2290.68     177 2291.49   202.5 2290.55     215    2291   227.4 2289.97
     239 2289.67   256.4 2291.37   268.9  2291.8   281.4 2290.97   300.9 2292.22
   335.2 2293.27   339.4 2293.97   347.7  2297.7   351.8 2299.07   363.4 2300.31
#Mann= 3 ,-1,0
       0     .06       0   147.4    .045       0   161.9      .1       0
Bank Sta=147.4,161.9
XS Rating Curve= 0 ,0
Exp/Cntr(USF)=0,0
Exp/Cntr=0.3,0.1

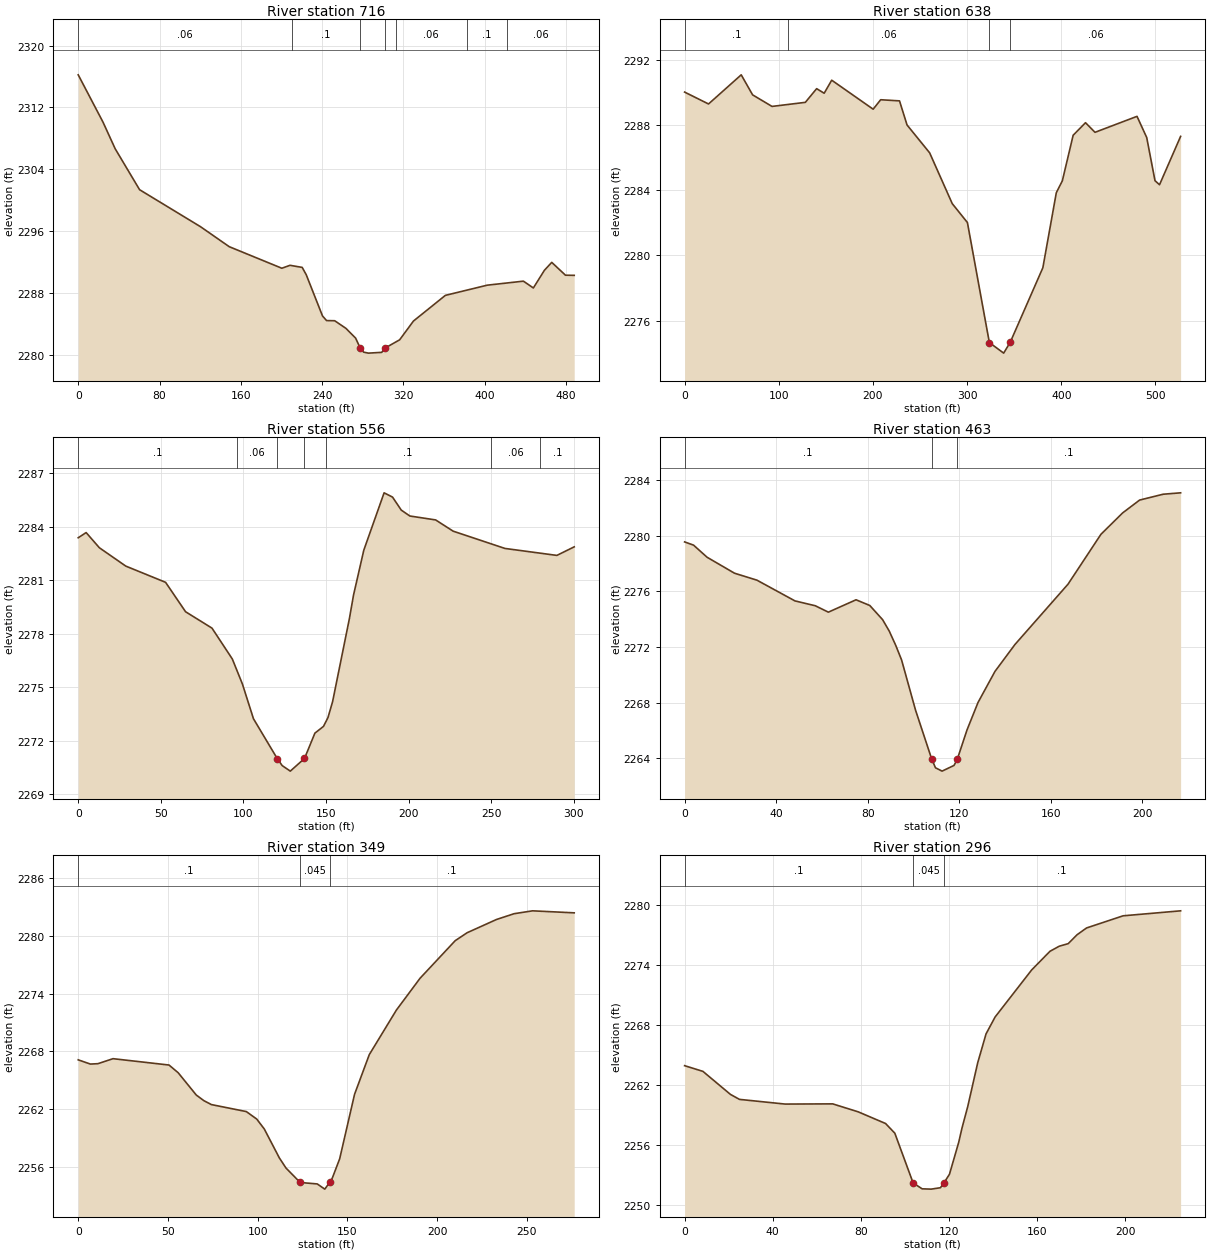
Type RM Length L Ch R = 1 ,716     ,78.5,78.5,78.2
XS GIS Cut Line= 4
2243402.25826938640852.7716590062243405.35343883 641125.76560389
2243421.44831993 641161.669569432243504.30981608641316.690620472
#Sta/Elev= 30
       0 2316.22    24.4  2310.1    36.4 2306.65    60.4 2301.36   120.4 2296.57
   148.6 2293.99   200.4  2291.2   208.4 2291.58   220.4 2291.31   224.4 2290.36
   240.4 2285.03   244.4 2284.43   252.4 2284.41   263.4 2283.43     273 2282.16
   277.52280.876   280.8 2280.35   285.5 2280.22   298.7 2280.32   301.9 2280.87
   316.3 2281.94   329.9 2284.37   361.3 2287.69   402.5 2289.01   438.1 2289.53
   447.9 2288.65   458.8 2290.94     466 2291.96   479.5  2290.3   488.1 2290.28
#Mann= 7 ,-1,0
       0     .06       0     210      .1       0   277.5    .045       0
   301.9      .1       0  312.36     .06       0  382.36      .1       0
  422.36     .06       0
Bank Sta=277.5,301.9
XS Rating Curve= 0 ,0
Exp/Cntr(USF)=0,0
Exp/Cntr=0.3,0.1

Type RM Length L Ch R = 1 ,638     ,87.4,81.9,80.9
XS GIS Cut Line= 4
2243326.11710108640849.0574556742243335.29861172 641159.55866387
2243353.34963991641199.2709258932243447.10274801641344.050522593
#Sta/Elev= 30
       0 2290.03    25.4  2289.3    60.1 2291.09    72.2 2289.86    92.8 2289.15
   128.2  2289.4   140.2 2290.24   148.2 2289.96   156.2 2290.76   200.2 2288.98
   208.2 2289.56   228.2 2289.49   236.2 2288.01   260.2  2286.3   284.2 2283.18
   300.3 2282.02   323.6 2274.65   338.8    2274   345.8 2274.67   380.4 2279.24
   394.7 2283.85   401.1 2284.58   412.6 2287.38   425.7 2288.15   435.8 2287.56
   480.4 2288.54   490.7 2287.24   499.5 2284.59   504.3 2284.34   526.7 2287.31
#Mann= 4 ,-1,0
       0      .1       0     110     .06       0   323.6    .045       0
   345.8     .06       0
Bank Sta=323.6,345.8
XS Rating Curve= 0 ,0
Exp/Cntr(USF)=0,0
Exp/Cntr=0.3,0.1

Type RM Length L Ch R = 1 ,556     ,91,92.7,93.6
XS GIS Cut Line= 4
2243248.35574532641120.4235707032243255.23389964641206.018379994
     2243284.362      641238.8852243394.28208777641369.214380876
#Sta/Elev= 30
       0 2283.38     4.8 2283.67    12.8 2282.82    28.8 2281.79    52.9 2280.88
      65 2279.23      81 2278.31    93.3 2276.58    99.4 2275.18   106.1 2273.23
   120.52270.994   123.5  2270.6   128.4 2270.29     137    2271   143.3 2272.42
   148.5  2272.8   151.2 2273.29     154 2274.18   164.2 2278.85   166.7 2280.17
   172.9 2282.68   185.2  2285.9   190.3 2285.66   195.6 2284.93   200.8  2284.6
   216.4 2284.38     227 2283.75   258.4 2282.78   289.8 2282.39   300.3 2282.87
#Mann= 7 ,-1,0
       0      .1       0   95.87     .06       0   120.5    .045       0
     137     .06       0  149.79      .1       0  249.79     .06       0
  279.79      .1       0
Bank Sta=120.5,137
XS Rating Curve= 0 ,0
Exp/Cntr(USF)=0,0
Exp/Cntr=0.3,0.1

Type RM Length L Ch R = 1 ,463     ,120.2,113.9,110
XS GIS Cut Line= 3
2243206.19612574641186.0033331722243178.33960075641242.273513648
2243261.90917572641371.527789594
#Sta/Elev= 30
       0 2279.56     3.9 2279.33     9.8 2278.46    21.8 2277.31    31.6 2276.81
    48.2 2275.32    57.1 2274.97    62.8 2274.51    74.9  2275.4    80.9 2274.99
    86.5 2273.97    89.4 2273.15    92.3  2272.1    94.8 2271.07   100.9 2267.46
   107.92263.975   109.6 2263.32   112.5 2263.08   117.7 2263.49   119.1 2263.92
   123.4 2266.05   128.2 2268.02   135.6 2270.25   144.3 2272.18   167.5 2276.52
   181.9 2280.11   191.4 2281.65   198.8 2282.57   209.1 2282.99   216.7 2283.09
#Mann= 3 ,-1,0
       0      .1       0   107.9    .045       0   119.1      .1       0
Bank Sta=107.9,119.1
XS Rating Curve= 0 ,0
Exp/Cntr(USF)=0,0
Exp/Cntr=0.3,0.1

Type RM Length L Ch R = 1 ,349     ,54.4,53.3,53.3
XS GIS Cut Line= 3
2243001.71694375641317.2800783722243132.52444285641360.596660042
2243266.63882344641395.469479006
#Sta/Elev= 30
       0 2267.11     6.8 2266.67      11 2266.71    19.4 2267.23    50.6 2266.57
    55.7 2265.77    65.8 2263.45      70 2262.87    74.2 2262.46    93.7 2261.73
    99.5 2260.95   103.7 2259.92   112.1 2256.91   115.8 2255.86   123.7 2254.36
   133.2 2254.21   137.4 2253.67   140.1 2254.36   141.6 2254.82   145.7 2256.82
     154 2263.53   162.2 2267.65   177.3 2272.28   190.5 2275.59   210.1  2279.5
   216.7 2280.32   233.1  2281.7   242.9  2282.3   253.2  2282.6   276.4 2282.39
#Mann= 3 ,-1,0
       0      .1       0   123.7    .045       0   140.1      .1       0
Bank Sta=123.7,140.1
XS Rating Curve= 0 ,0
Exp/Cntr=0.3,0.1

Type RM Length L Ch R = 1 ,296     ,99,99.6,99.8
XS GIS Cut Line= 2
2243012.12302927641382.7739398712243229.40392418641441.582159291
#Sta/Elev= 30
       0 2263.93     8.3 2263.36    20.8 2261.05    24.9 2260.55    45.6 2260.08
    67.2  2260.1    78.8  2259.3    91.2 2258.13    95.4 2257.16   103.7 2252.17
   107.8 2251.58   111.9 2251.55   116.1 2251.69   117.6 2252.15  117.63 2252.16
   120.2 2253.04   124.4 2256.25   125.9 2257.69   128.5 2259.84     133 2264.21
   136.8 2267.12   140.9 2268.81   157.5 2273.53   165.8  2275.4     170 2275.91
   174.1 2276.17   178.1 2277.06   182.4 2277.74     199 2278.96   225.1 2279.46
#Mann= 3 ,-1,0
       0      .1       0   103.7    .045       0  117.63      .1       0
Bank Sta=103.7,117.6
XS Rating Curve= 0 ,0
Exp/Cntr=0.3,0.1

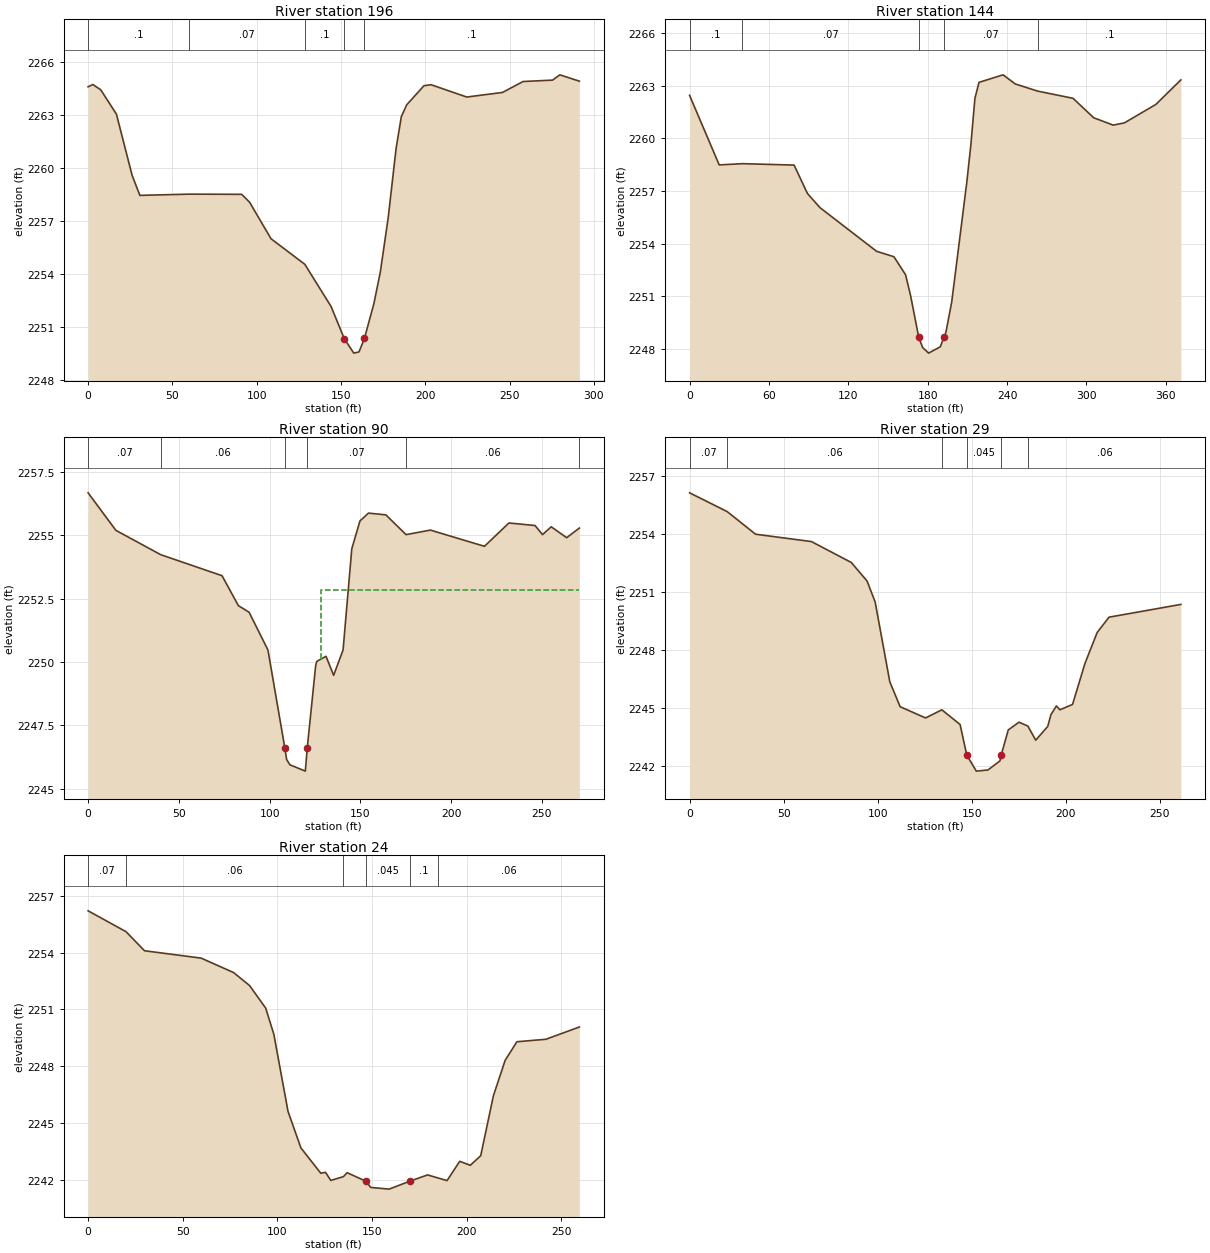
Type RM Length L Ch R = 1 ,196     ,51.6,52.6,53.9
XS GIS Cut Line= 3
2242995.34708678641398.764272584 2243050.6658387641492.151843032
2243223.16517265641552.824022558
#Sta/Elev= 30
       0 2264.61     2.8 2264.74     7.5 2264.44    16.8 2263.06    26.1 2259.59
    30.7 2258.45      60 2258.52    91.1 2258.51    95.8 2258.06   108.5 2255.99
  128.54 2254.54   144.1 2252.15  152.01 2250.31   157.6  2249.5   160.7 2249.57
   163.9 2250.33   169.5  2252.3   173.3 2254.08     178 2257.18   182.7 2261.12
   185.8 2262.92     189 2263.59   199.2 2264.67   203.4 2264.73   224.6 2264.03
   245.8 2264.29     258 2264.91   275.5 2264.99   279.8 2265.29   291.4 2264.93
#Mann= 5 ,-1,0
       0      .1       0      60     .07       0  128.54      .1       0
  152.01    .045       0   163.9      .1       0
Bank Sta=152.01,163.9
XS Rating Curve= 0 ,0
Exp/Cntr=0.3,0.1

Type RM Length L Ch R = 1 ,144     ,52.4,53.3,55.2
XS GIS Cut Line= 4
2242980.55230095641421.1540409662243040.59858814641540.008547583
2243205.88063641641612.4355125522243260.35561861641593.245462005
#Sta/Elev= 30
       0 2262.46    22.4 2258.49      40 2258.56      79 2258.48    89.1 2256.86
    98.6 2256.05   141.4 2253.56   154.5 2253.25   163.3 2252.22   167.1 2251.03
   173.2 2248.67   176.2 2248.07   180.7 2247.75   189.5 2248.11  192.41 2248.67
   193.8 2248.94   198.2 2250.68   209.6 2257.51   212.7 2259.67   215.7 2262.28
   218.8  2263.2     237 2263.63   246.2 2263.11  263.16  2262.7   289.9 2262.29
   305.5 2261.18   320.3 2260.76   328.8 2260.89   352.5 2261.94   371.4 2263.34
#Mann= 5 ,-1,0
       0      .1       0      40     .07       0   173.2    .045       0
  192.41     .07       0  263.16      .1       0
Bank Sta=173.2,192.41
XS Rating Curve= 0 ,0
Exp/Cntr=0.3,0.1

Type RM Length L Ch R = 1 ,90      ,59.3,61.5,65.5
XS GIS Cut Line= 4
 2243007.5778111641515.3407447582243042.85951389641589.214099335
2243091.83128482641629.3832083682243161.00850759641734.105357017
#Sta/Elev= 30
       0 2256.67    15.3 2255.19      40 2254.23    73.8  2253.4    82.8 2252.22
    88.7 2251.96    99.1 2250.47   108.4 2246.61   109.4 2246.15   111.2 2245.94
   119.7 2245.69  120.75  2246.6   125.4 2249.85     126 2250.02   131.1 2250.22
   135.3 2249.47   140.5 2250.47   145.3 2254.46   149.8 2255.56   154.5 2255.87
   164.1  2255.8   175.2 2255.02   188.6  2255.2   218.4 2254.56   231.9 2255.48
   246.3 2255.38   250.4 2255.02   255.2 2255.33   263.7  2254.9  270.71 2255.28
#Mann= 6 ,-1,0
       0     .07       0      40     .06       0   108.4    .045       0
  120.75     .07       0   175.2     .06       0  270.71      .1       0
#XS Ineff= 2 , 0
                          128.54         2252.84
Permanent Ineff=
       F       F
Bank Sta=108.4,120.75
XS Rating Curve= 0 ,0
Exp/Cntr=0.3,0.1

Type RM Length L Ch R = 1 ,29      ,5.3,5,5.7
XS GIS Cut Line= 6
2242980.76758763641532.0779907232243016.07675482641632.580993727
2243036.78896209641650.904927994 2243074.3133149641697.309548911
2243085.30765013641712.0225374832243116.24369788 641750.12722889
#Sta/Elev= 30
       0 2256.11      20 2255.14    35.1 2253.97    64.8 2253.59      86 2252.51
    94.4 2251.55    98.7 2250.47   106.5 2246.34     112 2245.05   125.5 2244.47
  134.18 2244.89   143.9 2244.13   147.4 2242.56   152.5 2241.72   158.7 2241.78
   165.1 2242.25  165.75 2242.55   169.5 2243.85   175.2 2244.25  179.94 2244.05
   184.1 2243.32   190.5 2244.03   192.2 2244.64   195.1 2245.09     197 2244.89
   203.7 2245.17   210.3 2247.29   216.8 2248.89   223.1 2249.68   261.3 2250.34
#Mann= 6 ,-1,0
       0     .07       0      20     .06       0  134.18      .1       0
   147.4    .045       0  165.75      .1       0  179.94     .06       0
Bank Sta=147.4,165.75
XS Rating Curve= 0 ,0
Exp/Cntr=0.3,0.1

Type RM Length L Ch R = 1 ,24      ,54.4,53.3,53.3
XS GIS Cut Line= 4
2242976.08119491641533.2945989172243012.85388257 641631.49156309
 2243089.3627304641720.3034612422243113.01943351641749.343882259
#Sta/Elev= 30
       0 2256.21      20 2255.11    29.8  2254.1    59.7 2253.71    76.8 2252.95
    85.3 2252.26    93.8 2251.07    98.1 2249.69   105.6 2245.61   112.4 2243.68
   122.9 2242.34   125.4 2242.39   128.2 2241.96  134.86 2242.16   136.8 2242.37
   146.7 2241.92   149.3 2241.59     159  2241.5  170.21 2241.93   179.3 2242.25
  184.86 2242.09   189.6 2241.95   196.3 2242.97   201.9 2242.76   207.4 2243.27
   214.1 2246.44   220.3 2248.31   226.5 2249.29   241.8 2249.42   259.5 2250.07
#Mann= 6 ,-1,0
       0     .07       0      20     .06       0  134.86      .1       0
   146.7    .045       0  170.21      .1       0  184.86     .06       0
Bank Sta=146.7,170.21
XS Rating Curve= 0 ,0
Exp/Cntr(USF)=0,0
Exp/Cntr=0.3,0.1
LCMann Table=0

Chan Stop Cuts=-1
Use User Specified Reach Order=0
Composite Channel Slope=5